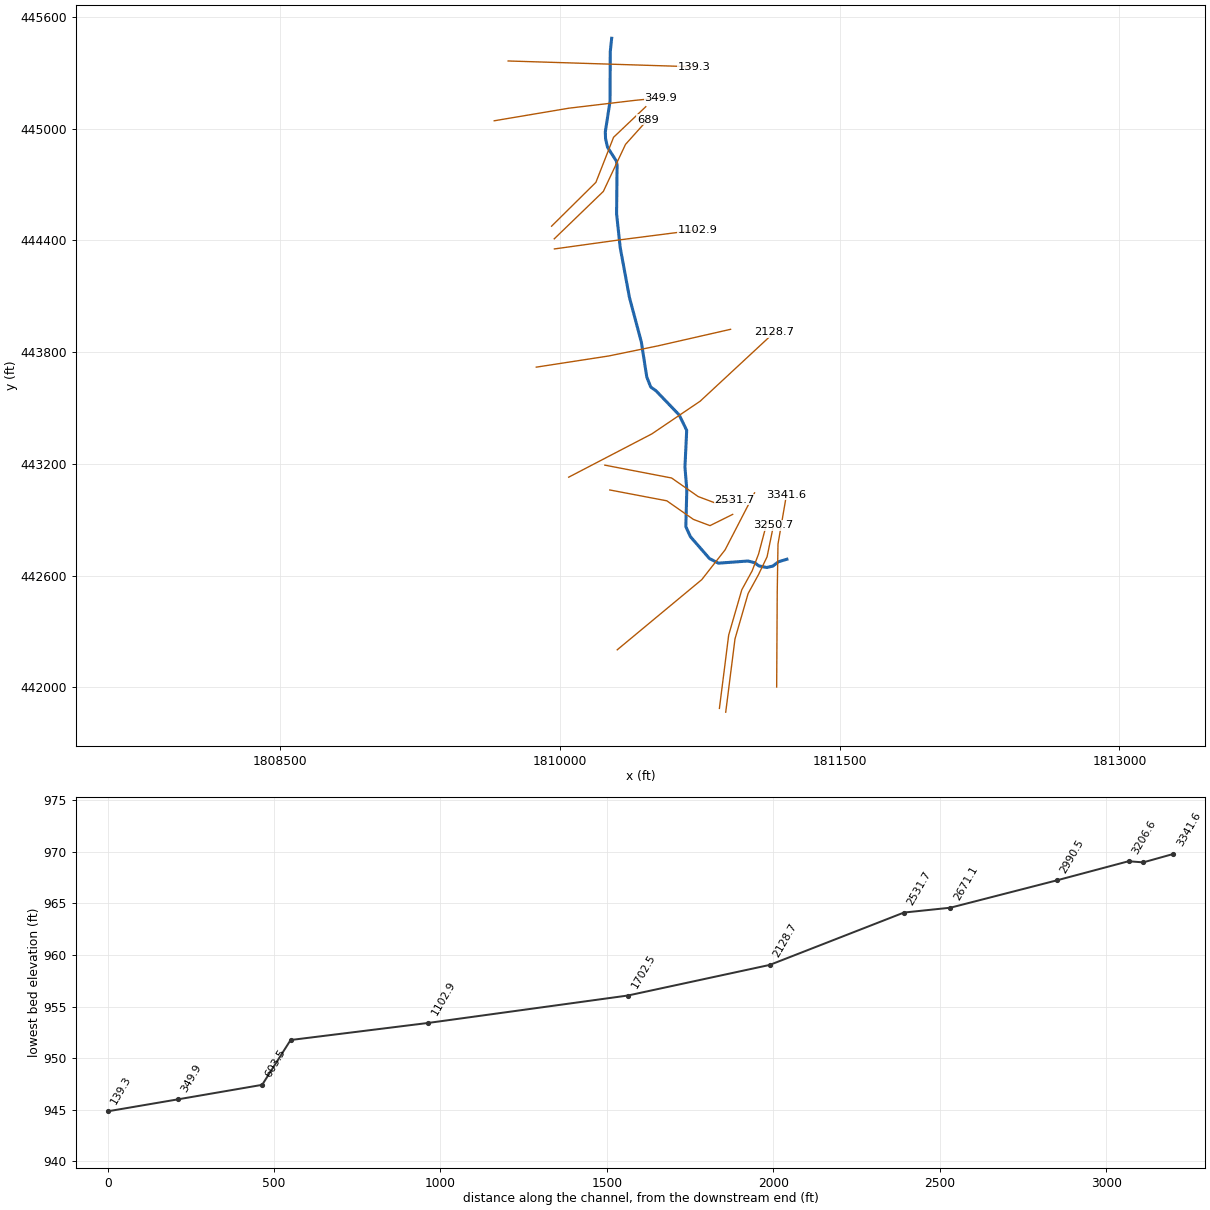
--- T3DunkCk.prj (project) ---

Proj Title=T3DunkCk
Current Plan=p01
Default Exp/Contr=0,0
English Units
Geom File=g01
Flow File=f01
Plan File=p01
BEGIN DESCRIPTION:
END DESCRIPTION:
DSS Export Rating Curves= 0
DSS Export Rating Curve Sorted= 0
DSS Export Volume Flow Curves= 0
DXF OffsetX= 0
DXF OffsetY= 0
DXF ScaleX= 0
DXF ScaleY= 0

--- T3DunkCk.p01 (plan) ---

Plan Title=Floodplain
Program Version=4.00
Geom File=g01
Flow File=f01
K Sum by GR=0
Std Step Tol=0.01
Critical Tol=0.01
Num of Std Step Trials=20
Max Error Tol=0.3
Flow Tol Ratio=0.001
Split Flow NTrial=30
Split Flow Tol=0.02
Split Flow Ratio=0.02
Log Output Level=0
Friction Slope Method=1
Unsteady Friction Slope Method=2
Unsteady Bridges Friction Slope Method=1
Global Log Level=0
CheckData=False
Run HTab=0
Run UNet=0
Run PostProcess=0
UNET Theta=0
UNET Theta Warmup=0
UNET ZTol=0
UNET ZSATol=0
UNET MxIter=0
UNET MaxInSteps=0
UNET DtIC=0
UNET DtMin=0
UNET MaxCRTS=0
UNET WFStab=0
UNET SFStab=0
UNET WFX=0
UNET SFX=0
UNET DSS MLevel=0
UNET DZMax Abort=0
UNET Convert EG Bridges=0
UNET Use Existing IB Tables=0
UNET Froude Limit=0
UNET Froude Power=0
Write IC File=0
Echo Input=False
Echo Output=False
Write Detailed=0

--- T3DunkCk.f01 (steady flow) ---

Flow Title=NFF Regression Equation
Program Version=4.10
Number of Profiles= 1
Profile Names=P100yr
River Rch & RM=T3DunkCk,Main            ,3341.6
     782
River Rch & RM=T3DunkCk,Main            ,3250.7
    1223
River Rch & RM=T3DunkCk,Main            ,2128.7
    1241
River Rch & RM=T3DunkCk,Main            ,1702.5
    1393
River Rch & RM=T3DunkCk,Main            ,139.3
    1453
Boundary for River Rch & Prof#=T3DunkCk,Main            , 1
Up Type= 0
Dn Type= 3
Dn Slope=0.00559
DSS Import GetInterval= 0
DSS Import GetPeak= 0
DSS Import FillOption= 0

--- T3DunkCk.g01 (geometry) ---

Geom Title=USGS 10m DEM
Program Version=4.10

River Reach=T3DunkCk        ,Main
Reach XY= 30
     1811217.293      442687.924     1811171.286      442674.036
      1811142.64      442651.466     1811109.476      442643.697
     1811067.115       442652.03     1811044.198      442669.391
     1811008.781      442678.419     1810850.356      442666.845
     1810802.493      442691.441     1810700.121      442809.103
     1810675.525      442862.948     1810680.842      443059.717
     1810670.871      443183.362     1810680.178      443380.264
     1810640.049      443462.694     1810516.049      443592.056
     1810487.464      443612.664     1810466.192      443666.509
     1810436.942      443854.636     1810373.458      444092.752
     1810323.601      444362.379     1810304.323      444542.528
     1810306.982      444804.177     1810302.993      444826.114
     1810255.796      444900.035      1810245.16      444946.569
      1810243.83      444982.466     1810269.091      445145.996
     1810270.512      445413.768     1810277.971      445485.375

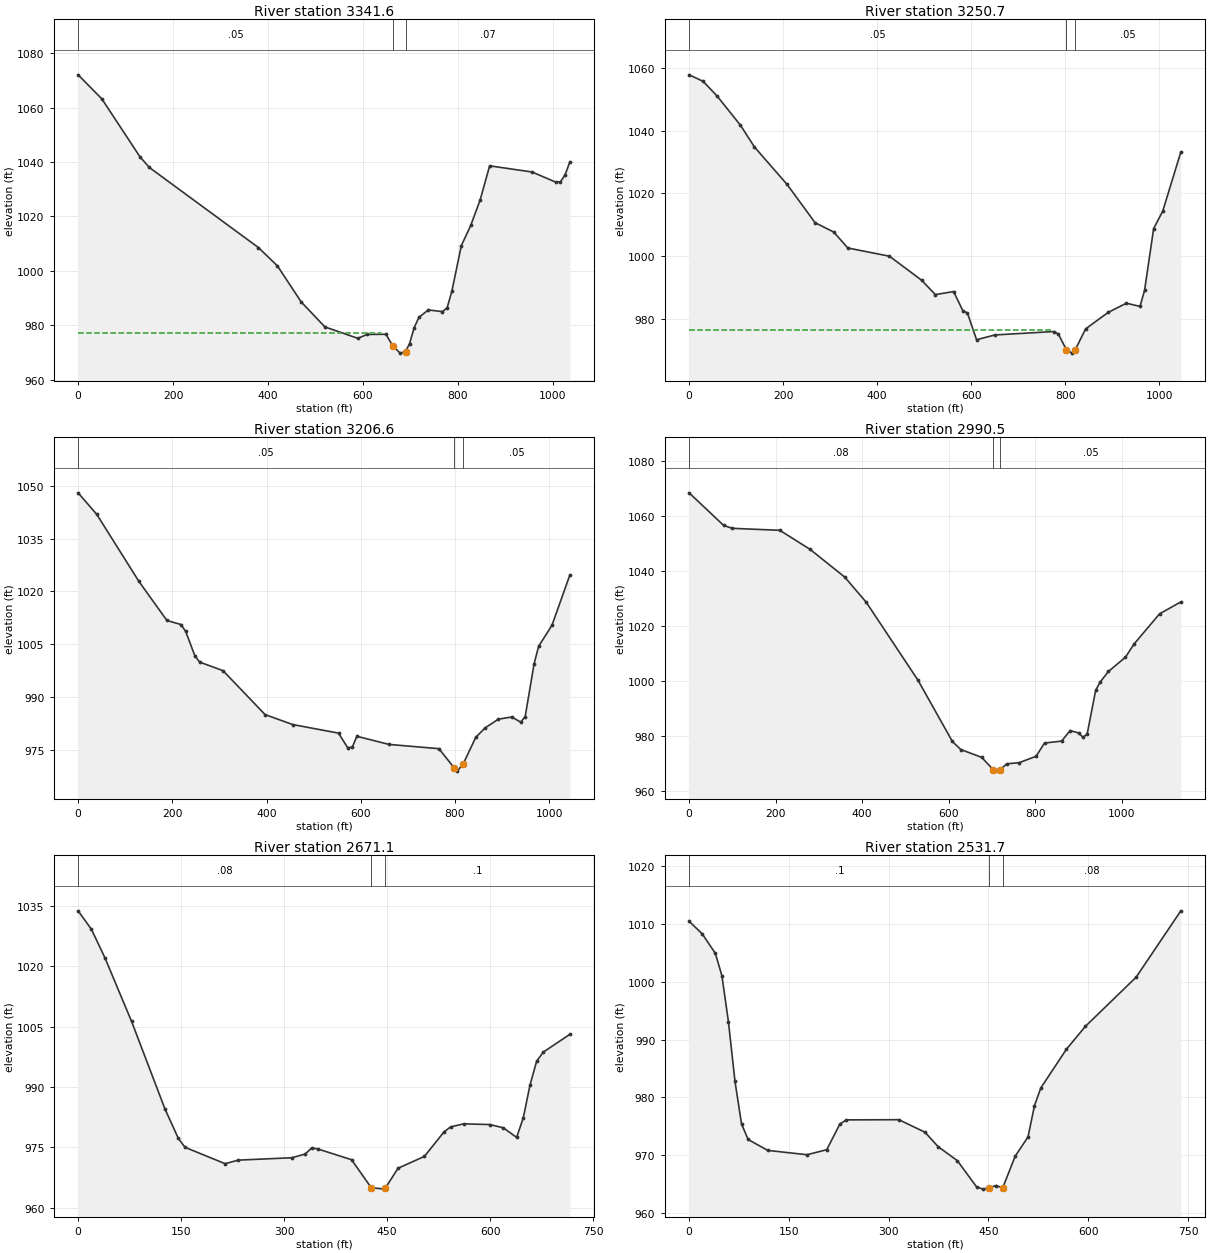
Type RM Length L Ch R = 1 ,3341.6  ,97.9,90.9,81.7
XS GIS Cut Line= 4
     1811162.575      442001.719     1811165.613      442511.702
     1811169.699      442769.174     1811215.093      443033.837
#Sta/Elev= 30
       0 1072.02      50 1063.18     130 1041.99     150    1038     380 1008.56
     420 1001.83     470  988.61   519.9  979.44   589.2  975.25     609  976.67
   648.6  976.74   662.4   972.6   678.4  969.81  689.78  970.38   698.2  973.25
   708.1  979.19     718  982.96   737.8  985.67   767.5  985.05   777.4  986.42
   787.4  992.54   807.3 1009.26   827.2 1016.71   847.1 1026.13     867  1038.6
   956.5 1036.33  1006.2 1032.61  1016.1  1032.7  1026.1 1035.37    1036 1040.05
#Mann= 3 , 0 , 0
       0     .05       0   662.4    .045       0  689.78     .07       0
#XS Ineff= 2 , 0
          638.13  977.04
Permanent Ineff=
       F       F
Bank Sta=662.4,689.78
XS Rating Curve= 0 ,0
Exp/Cntr=0.3,0.1

Type RM Length L Ch R = 1 ,3250.7  ,42.2,44.1,46.4
XS GIS Cut Line= 6
     1810889.447       441866.61     1810939.187       442260.36
     1811009.543      442503.766     1811065.098      442605.328
     1811111.105      442700.814     1811145.828      442870.953
#Sta/Elev= 30
       0 1057.81    29.8 1055.74    59.5 1051.05   109.1 1041.75   138.9  1034.8
   208.4 1022.82   267.9 1010.62   307.6 1007.63   337.4 1002.55   426.1  999.92
   494.3  992.27   523.6  987.67   562.5  988.64     582  982.55   591.8   981.8
   611.3  973.26   650.2  974.79   775.6  975.88   785.3  975.07  802.14  970.09
   814.2  968.99   820.4  969.86   843.1  976.72   891.3  982.01   929.9  984.92
   958.8   983.9   968.5  989.02   987.8 1008.76  1007.1  1014.3  1045.6 1033.18
#Mann= 3 , 0 , 0
       0     .05       0  802.14    .045       0   820.4     .05       0
#XS Ineff= 2 , 0
          772.34  976.22
Permanent Ineff=
       F       F
Bank Sta=802.14,820.4
XS Rating Curve= 0 ,0
Exp/Cntr=0.3,0.1

Type RM Length L Ch R = 1 ,3206.6  ,223,216.1,208.9
XS GIS Cut Line= 6
     1810855.593      441887.009     1810905.333      442280.759
     1810975.689      442524.165     1811031.244      442625.728
     1811065.923      442717.044     1811111.973      442891.353
#Sta/Elev= 30
       0 1047.95    39.7 1041.82     129 1022.86   188.5 1011.78   218.3 1010.64
   228.2 1008.72     248 1001.74     258  999.99   307.6  997.57   396.9  985.12
   455.4   982.3   552.8  979.87   572.3  975.73     582  975.87   591.8  978.97
   659.9  976.67     766  975.46  798.62     970   805.1   969.1   817.9  971.24
   844.2  978.67   863.7  981.31   892.2  983.82   920.6  984.44   939.6  982.98
   949.1  984.54   968.1   999.5   977.6 1004.45    1006 1010.42    1044 1024.67
#Mann= 3 , 0 , 0
       0     .05       0  798.62    .045       0   817.9     .05       0
Bank Sta=798.62,817.9
XS Rating Curve= 0 ,0
Exp/Cntr=0.3,0.1

Type RM Length L Ch R = 1 ,2990.5  ,355.5,319.3,283
XS GIS Cut Line= 4
      1810307.85       442201.68     1810760.975      442578.416
     1810885.975      442738.138     1811043.831      443044.304
#Sta/Elev= 30
       0 1068.59    79.9 1056.72    99.9 1055.66   209.7 1054.94   279.7    1048
   359.6 1037.93   409.5 1028.73   529.4 1000.26   608.6  978.03   627.9  975.11
   676.2  972.27   703.5  967.68   714.8  967.24   718.5  967.73   734.2  969.89
   763.1  970.32   801.9  972.64   821.6  977.47     861  978.17   880.7  982.01
   900.4  981.15   910.2   979.6     920  980.67   939.7  996.61   949.6  999.57
   969.3 1003.54  1008.6 1008.72  1028.3  1013.5  1087.4 1024.52  1136.6 1028.86
#Mann= 3 , 0 , 0
       0     .08       0   703.5    .045       0   718.5     .05       0
Bank Sta=703.5,718.5
XS Rating Curve= 0 ,0
Exp/Cntr=0.3,0.1

Type RM Length L Ch R = 1 ,2671.1  ,140.6,139.4,138
XS GIS Cut Line= 5
     1810267.789      443059.929     1810573.562      443001.708
     1810716.097      442901.986     1810805.159      442868.393
      1810926.73      442928.748
#Sta/Elev= 30
       0 1033.77    19.4 1029.16    38.9 1022.14    77.8  1006.3   126.4  984.54
   145.9  977.21   155.6  974.99     214  970.92   233.4   971.8   311.3  972.39
   330.6  973.31   340.3  974.85   349.9  974.53   398.2   971.9  426.81  964.95
   446.6  964.59  447.05  964.76   465.9  969.78   504.3  972.73   532.8   978.8
   542.3  980.05   561.4  980.82   599.8  980.64   619.2  979.83   638.6  977.45
   648.3  982.32     658  990.41   667.7  996.39   677.4  998.65   716.1 1003.07
#Mann= 3 , 0 , 0
       0     .08       0  426.81    .045       0  447.05      .1       0
Bank Sta=426.81,447.05
XS Rating Curve= 0 ,0
Exp/Cntr=0.3,0.1

Type RM Length L Ch R = 1 ,2531.7  ,372.6,403,433.2
XS GIS Cut Line= 5
     1810241.401      443193.216     1810599.343      443124.191
     1810741.878      443024.469      1810830.94      442990.875
     1810935.194      443007.018
#Sta/Elev= 30
       0 1010.46    19.7 1008.28    39.4 1004.91    49.3 1001.05    59.1   993.1
      69  982.75    78.8  975.41    88.7  972.71   118.2  970.82   177.3  970.07
   206.9  970.94   226.6  975.36   236.5   976.1   315.3  976.13   354.7  973.96
   374.2  971.48   403.2  969.05   432.2   964.5   441.8  964.12   451.5  964.37
   461.2  964.74   471.5  964.35   490.2  969.82   509.5  973.15   519.2  978.57
   528.8  981.64     567  988.28   595.6  992.26     672 1000.78   739.2 1012.26
#Mann= 3 , 0 , 0
       0      .1       0   451.5    .045       0   471.5     .08       0
Bank Sta=451.5,471.5
XS Rating Curve= 0 ,0
Exp/Cntr=0.3,0.1

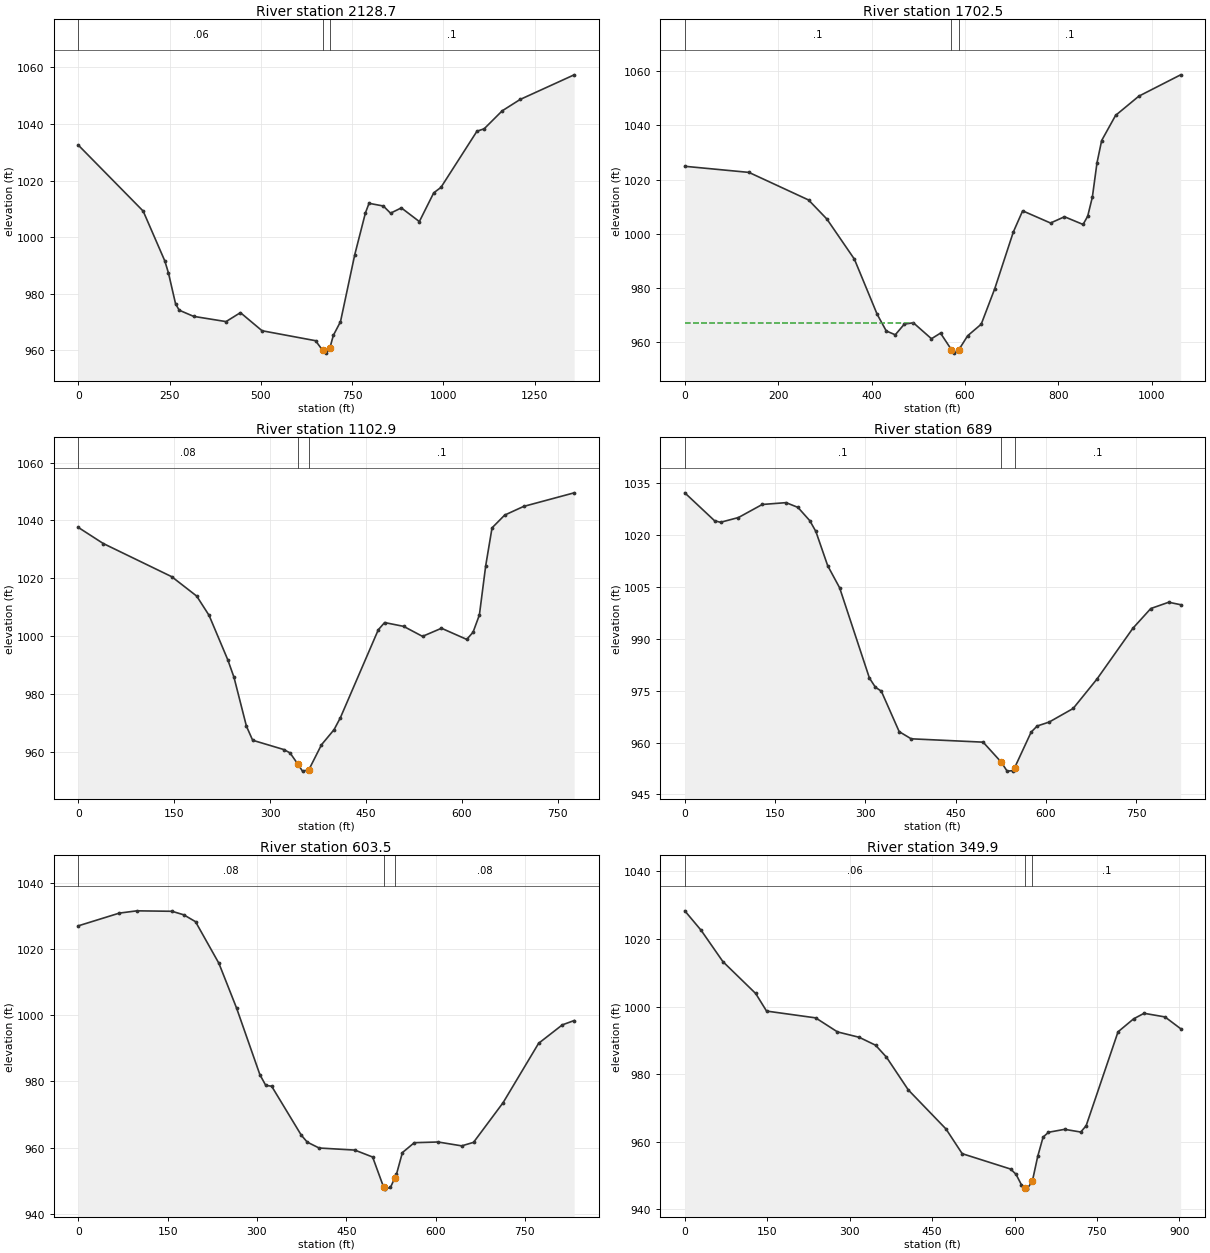
Type RM Length L Ch R = 1 ,2128.7  ,435.3,426.2,416.9
XS GIS Cut Line= 4
     1810047.434      443128.534     1810493.614      443361.173
     1810752.295       443536.52     1811149.459      443905.743
#Sta/Elev= 30
       0 1032.52   177.6 1009.22   236.8  991.63   246.7  987.42   266.4  976.42
   276.3  974.21   315.7  972.03   404.5  970.18     444  973.34   503.2  966.95
   649.7  963.43   669.2  960.02     679  959.04   688.6  960.71   698.5  965.34
     718  970.14   757.1  993.82   786.4 1008.62   796.2 1011.97   835.4 1011.01
   855.1 1008.48   884.7 1010.35     934 1005.52   973.4 1015.67   993.2  1017.6
  1091.8 1037.44  1111.5 1038.29  1160.8 1044.63  1210.1 1048.66    1358 1057.36
#Mann= 3 , 0 , 0
       0     .06       0   669.2    .045       0   688.6      .1       0
Bank Sta=669.2,688.6
XS Rating Curve= 0 ,0
Exp/Cntr=0.3,0.1

Type RM Length L Ch R = 1 ,1702.5  ,601,599.6,597.9
XS GIS Cut Line= 4
     1809873.692      443719.434     1810261.713       443779.33
     1810527.338      443834.018     1810915.359      443922.559
#Sta/Elev= 30
       0 1024.87   137.4 1022.62     265 1012.47   304.3 1005.44   363.2  990.67
     412  970.35   431.4  964.24   450.7  962.82   470.1  966.75   489.5  967.24
   528.2  961.37   547.6  963.44   570.8  957.39   576.6  956.07   586.3  957.17
   605.7  962.46   634.8  966.73   663.8  979.82   703.6 1000.71   723.5 1008.47
   783.2 1003.98   813.1 1006.29   852.9 1003.45   862.8  1006.5   872.8 1013.53
   882.7 1026.14   892.7 1034.36   922.5 1043.61   972.3 1050.69  1061.8 1058.55
#Mann= 3 , 0 , 0
       0      .1       0   570.8    .045       0   586.3      .1       0
#XS Ineff= 2 , 0
          490.51  967.17
Permanent Ineff=
       F       F
Bank Sta=570.8,586.3
XS Rating Curve= 0 ,0
Exp/Cntr=0.3,0.1

Type RM Length L Ch R = 1 ,1102.9  ,376.1,413.9,441.5
XS GIS Cut Line= 3
     1809971.045      444354.229     1810318.508      444402.525
     1810740.142      444456.659
#Sta/Elev= 30
       0  1037.6      39 1032.05   146.2 1020.58   185.2 1013.89   204.6 1007.22
   233.9  991.86   243.6  985.81   263.1   968.9   272.8  964.08   321.6  960.86
   331.3   959.7   343.3   955.9   350.8  953.41   360.7  953.87   380.5  962.52
   400.2  967.74   410.1  971.88   469.4 1002.25   479.3 1004.74     509 1003.43
   538.6  999.97   568.3 1002.77   607.8  998.92   617.7 1001.41   627.6 1007.37
   637.5  1024.4   647.4 1037.46   667.2 1041.87   696.8 1044.86   775.9 1049.56
#Mann= 3 , 0 , 0
       0     .08       0   343.3    .045       0   360.7      .1       0
Bank Sta=343.3,360.7
XS Rating Curve= 0 ,0
Exp/Cntr=0.3,0.1

Type RM Length L Ch R = 1 ,689     ,96.8,85.5,85.7
XS GIS Cut Line= 4
     1809970.093      444408.389     1810233.299      444663.011
     1810352.222      444915.615     1810471.363      445048.644
#Sta/Elev= 30
       0 1032.25    49.5 1024.17    59.4 1023.73    89.1  1025.1   128.7 1028.88
   168.3 1029.41     188 1028.04   207.8 1024.18   217.8 1021.08   237.5 1011.16
   257.3 1004.78   306.8  978.68   316.7  976.03   326.6  974.88   356.3  963.17
   376.2   961.1   495.8  960.13   525.8  954.37   535.7  951.75   545.7  951.89
  548.26  952.78   575.6  963.04   585.6   964.8   605.5  965.94   645.4  969.87
   685.1  978.41   744.6  993.06   774.4  998.78   804.2  1000.6     824  999.89
#Mann= 3 , 0 , 0
       0      .1       0   525.8    .045       0  548.26      .1       0
Bank Sta=525.8,548.26
XS Rating Curve= 0 ,0
Exp/Cntr=0.3,0.1

Type RM Length L Ch R = 1 ,603.5   ,280.1,253.6,225.2
XS GIS Cut Line= 4
      1809955.81      444476.379      1810193.44      444711.839
     1810288.094      444953.665     1810460.946      445118.089
#Sta/Elev= 30
       0 1027.12    68.9 1030.97    98.4 1031.66   157.4 1031.52   177.1 1030.45
   196.8 1028.38   236.1 1015.77   265.7 1002.26     305  982.03   314.8  978.81
   324.7  978.56   374.5  963.73   384.5  961.63   404.4  959.85   464.4  959.22
   494.3  957.12  512.79  947.99   514.3   947.4   524.3  947.93   531.8  950.88
   534.3  951.86   544.3  958.46   564.3  961.46   604.2  961.67   643.9   960.5
   663.8  961.56   713.5  973.59   773.1  991.55   812.9  997.13   832.8  998.44
#Mann= 3 , 0 , 0
       0     .08       0  512.79    .045       0   531.8     .08       0
Bank Sta=512.79,531.8
XS Rating Curve= 0 ,0
Exp/Cntr=0.3,0.1

Type RM Length L Ch R = 1 ,349.9   ,213.9,210.6,207.1
XS GIS Cut Line= 4
     1809648.229      445042.351     1810049.271      445110.059
     1810399.965      445151.726     1810541.675      445165.832
#Sta/Elev= 30
       0 1028.33    29.8 1022.55    69.4 1013.29     129 1003.87   148.8  998.67
   238.1  996.66   277.8  992.51   317.4  990.91   347.2  988.57     367  985.03
   406.7  975.35   475.4  963.77   504.8  956.48   593.1  951.92   602.9  950.34
   612.7  947.24   619.5  946.37   622.5  945.99   632.4  948.28   642.2  955.65
     652  961.37   661.8  962.81   691.2  963.68   720.6  962.88   730.4  964.76
   788.4  992.53   816.8  996.38   835.8  998.01   873.8  996.94   902.3  993.46
#Mann= 3 , 0 , 0
       0     .06       0   619.5    .045       0   632.4      .1       0
Bank Sta=619.5,632.4
XS Rating Curve= 0 ,0
Exp/Cntr=0.3,0.1

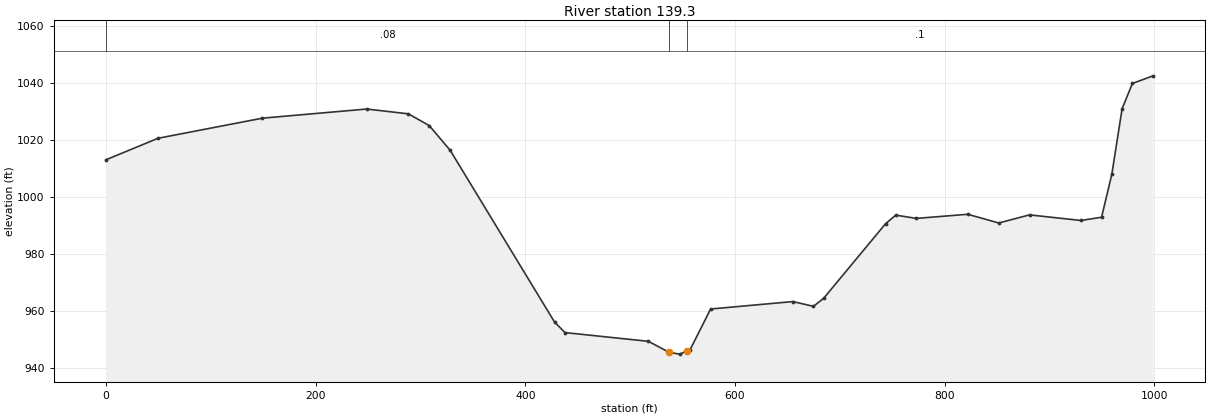
Type RM Length L Ch R = 1 ,139.3   ,141,139.3,137.7
XS GIS Cut Line= 3
     1809722.882      445363.531      1810269.95       445346.42
     1810721.146      445332.281
#Sta/Elev= 30
       0 1013.13    49.8  1020.7   149.3 1027.76   248.8 1030.97   288.6 1029.28
   308.5 1025.12   328.4 1016.45   427.9  956.12   437.9   952.4   517.5  949.33
   537.4  945.42   547.3  944.83   554.2   945.9   557.2  946.37   576.8  960.69
   655.3   963.3   674.9  961.62   684.7  964.48   743.6  990.64   753.4  993.69
     773  992.53   822.1  993.98   851.6  990.92     881  993.77   930.1   991.8
   949.7  992.94   959.5  1008.1   969.3  1031.1   979.1 1039.95   998.8 1042.64
#Mann= 3 , 0 , 0
       0     .08       0   537.4    .045       0   554.2      .1       0
Bank Sta=537.4,554.2
XS Rating Curve= 0 ,0
Exp/Cntr=0.3,0.1

Chan Stop Cuts=-1
Use User Specified Reach Order=0
Composite Channel Slope=5